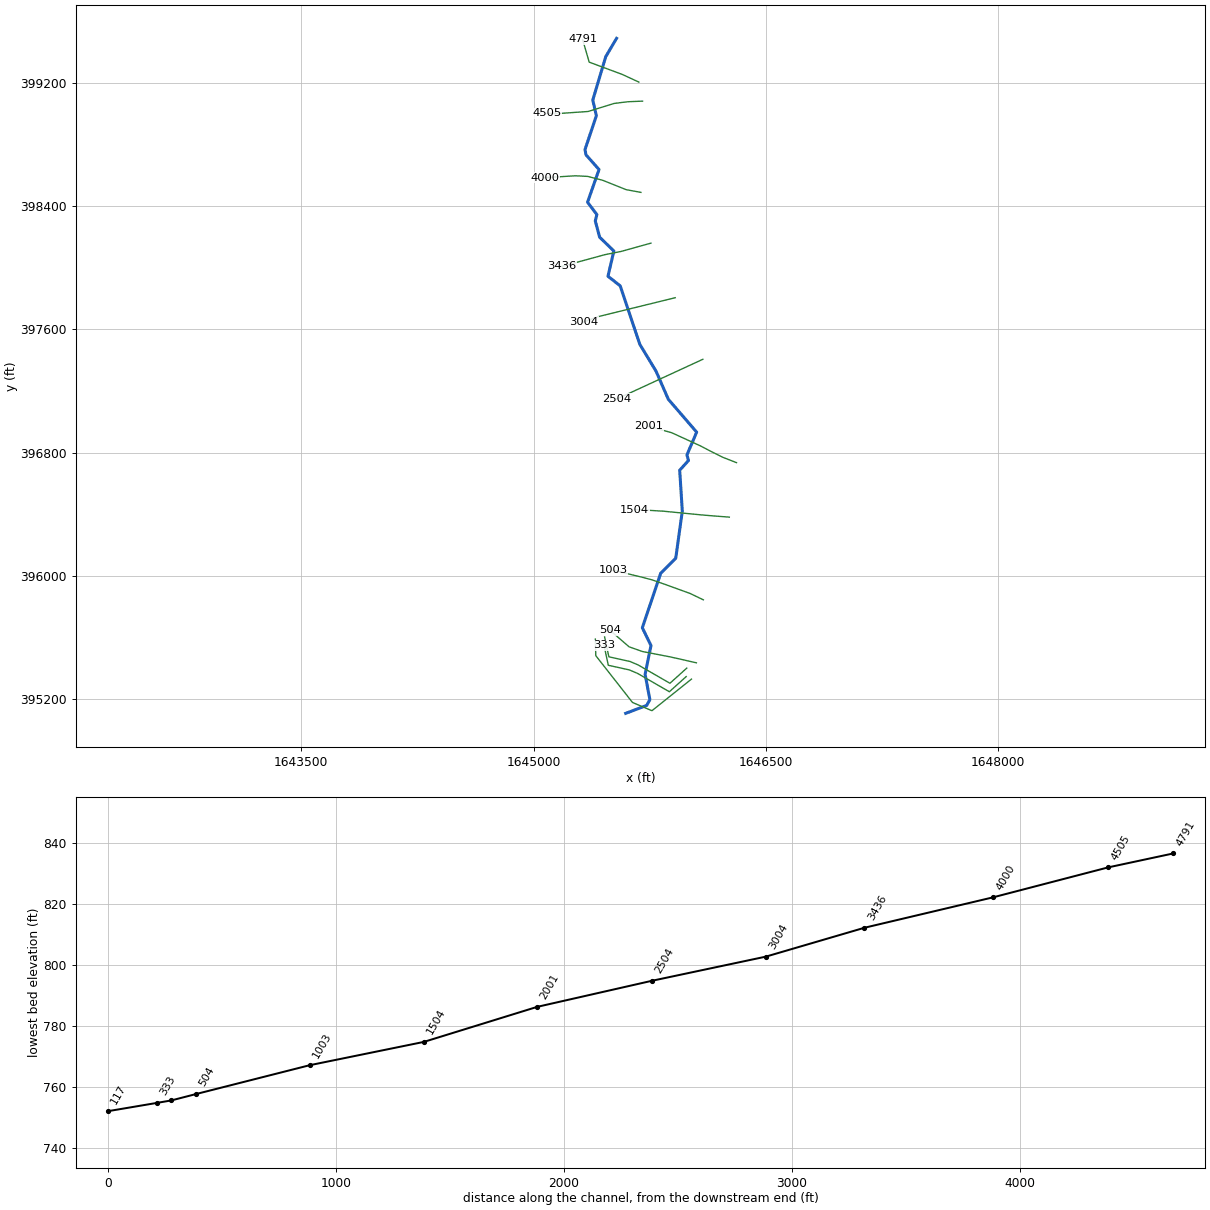
--- BETSYRN.prj (project) ---

Proj Title=BETSYRN
Current Plan=p01
Default Exp/Contr=0,0
English Units
Geom File=g01
Flow File=f01
Plan File=p01
BEGIN DESCRIPTION:
---------- MODELED AS PART OF WVEMD CTP PROGRAM, 2023----------
Stream Name: Betsy Run
Flood Zone:  AFH
Wetzel County, WV
HEC-RAS Version: RAS 6.3
Vertical Datum: NAVD88
Projection: NAD 1983 StatePlane West Virginia S FIPS 4702 (US Feet)
Terrain: 1-meter West Virginia FEMA R3 South Central (collected 2018-2020)
Land Use: 2019 NLCD
Hydrologic Method:
WV 2010 Regional Regression Equations
Additional Model Notes:
None
END DESCRIPTION:
DSS Export Rating Curves= 0
DSS Export Rating Curve Sorted= 0
DSS Export Volume Flow Curves= 0
DXF OffsetX= 0
DXF OffsetY= 0
DXF ScaleX= 0
DXF ScaleY= 0

--- BETSYRN.p01 (plan) ---

Plan Title=Floodplain
Program Version=6.30
Short Identifier=Floodplain
Geom File=g01
Flow File=f01
Subcritical Flow
K Sum by GR= 0
Std Step Tol= 0.01
Critical Tol= 0.01
Num of Std Step Trials= 20
Max Error Tol= 0.3
Flow Tol Ratio= 0.001
Split Flow NTrial= 30
Split Flow Tol= 0.02
Split Flow Ratio= 0.02
Log Output Level= 0
Friction Slope Method= 1
Unsteady Friction Slope Method= 2
Unsteady Bridges Friction Slope Method= 1
Parabolic Critical Depth
Global Vel Dist= 0 , 0 , 0
Global Log Level= 0
CheckData=True
Encroach Param=-1 ,0,0, 0
Mapping Interval=1HOUR
Computation Time Step Use Courant=        0
Computation Time Step Use Time Series=    0
Computation Time Step Count To Double=0
Computation Time Step Max Doubling=0
Computation Time Step Max Halving=0
Computation Time Step Residence Courant=0
Run HTab= 0
Run UNet= 0
Run Sediment= 0
Run PostProcess= 0
Run WQNet= 0
Run RASMapper=-1
UNET Theta= 0
UNET Theta Warmup= 0
UNET ZTol= 0
UNET ZSATol= 0
UNET MxIter= 0
UNET Max Iter WO Improvement= 0
UNET MaxInSteps= 0
UNET DtIC= 0
UNET DtMin= 0
UNET MaxCRTS= 0
UNET WFStab= 0
UNET SFStab= 0
UNET WFX= 1
UNET SFX= 1
UNET Gravity=32.17405
UNET 1D Methodology=Finite Difference
UNET DSS MLevel= 1
UNET Pardiso=0
UNET DZMax Abort= 0
UNET Use Existing IB Tables= 0
UNET Froude Reduction=False
UNET Froude Limit= 0
UNET Froude Power= 0
UNET D1 Cores= 0
UNET WindReference=Eulerian
UNET WindDragFormulation=Hsu (1988)
UNET D2 Coriolis=0
UNET D2 Cores= 0
UNET D2 Theta= 1
UNET D2 Theta Warmup= 1
UNET D2 Z Tol= 0.01
UNET D2 Volume Tol= 0.01
UNET D2 Max Iterations= 20
UNET D2 Equation= 0
UNET D2 RampUpFraction=0.1
UNET D2 TimeSlices= 1
UNET D2 Turbulence Formulation=Non-Conservative (original)
UNET D2 Eddy Viscosity=0.3
UNET D2 Transverse Eddy Viscosity=0.1
UNET D2 Smagorinsky Mixing=0
UNET D2 BCVolumeCheck=0
UNET D2 Cores=0
UNET D2 SolverType=PARDISO (Direct)
UNET D2 Minimum Iterations= 3
UNET D2 Maximum Iterations= 30
UNET D2 Restart Number= 10
UNET D2 Relaxation Coeff=1.3
UNET D2 SOR Precondition Iterations= 10
UNET D2 ILUT Maximum Fill= 8
UNET D2 ILUT Tolerance=1E-08
UNET D2 Convergence Tolerance=0.00001
UNET D1D2 MaxIter= 0
UNET D1D2 ZTol=0.01
UNET D1D2 QTol=0.1
UNET D1D2 MinQTol=1
Write IC File= 0
Write IC File at Fixed DateTime=0
Write IC File at Sim End=0
Echo Input=False
Echo Parameters=False
Echo Output=False
Write Detailed= 0
HDF Write Warmup=0
HDF Write Time Slices=0
HDF Flush=0
HDF Compression= 1
HDF Chunk Size= 1
HDF Spatial Parts= 1
HDF Use Max Rows=0
HDF Fixed Rows= 1
Calibration Method= 0
Calibration Iterations= 20
Calibration Max Change=0.05
Calibration Tolerance=0.2
Calibration Maximum=1.5
Calibration Minimum=0.5
Calibration Optimization Method= 1
WQ AD Non Conservative
WQ ULTIMATE=-1
WQ Max Comp Step=1HOUR
WQ Output Interval=15MIN
WQ Output Selected Increments= 0
WQ Output face flow=0
WQ Output face velocity=0
WQ Output face area=0
WQ Output face dispersion=0
WQ Output cell volume=0
WQ Output cell surface area=0
WQ Output cell continuity=0
WQ Output cumulative cell continuity=0
WQ Output face conc=0
WQ Output face dconc_dx=0
WQ Output face courant=0
WQ Output face peclet=0
WQ Output face adv mass=0
WQ Output face disp mass=0
WQ Output cell mass=0
WQ Output cell source sink temp=0
WQ Output nsm pathways=0
WQ Output nsm derived pathways=0
WQ Create Restart=0
WQ Fixed Restart=0
WQ System Summary=0
WQ Write To DSS=0
Sorting and Armoring Iterations= 10
XS Update Threshold= 0.02
Bed Roughness Predictor= 0
Hydraulics Update Threshold= 0.02
Energy Slope Method= 1
Volume Change Method= 1
Sediment Retention Method= 0
Sediment TS Multiplier= 1
Warm Up Method= 0
XS Weighting Method= 0
Number of US Weighted Cross Sections= 1
Number of DS Weighted Cross Sections= 1
Upstream XS Weight=0
Main XS Weight=1
Downstream XS Weight=0
Number of DS XS's Weighted with US Boundary= 1
Upstream Boundary Weight= 1
Weight of XSs Associated with US Boundary= 0
Number of US XS's Weighted with DS Boundary= 1
Downstream Boundary Weight= 0.5
Weight of XSs Associated with DS Boundary= 0.5
Percentile Method= 0
Sediment Output Level= 3
Mass or Volume Output= 0
Output Increment Type= 1
Profile and TS Output Increment= 1
Transport Output Increment 1
XS Output Flag= 0
XS Output Increment= 10
Read HDF5 Sediment Hotstart= 0
Sediment Hotstart Type= 0
Write Gradation File= 0
Read Gradation Hotstart= 0
Write HDF5 File= 1
Write Binary Output= 1
Write DSS Sediment File= 0
DSS Sediment Output Type= 1
SV Curve= 0
Specific Gage Flag= 0
Subcell Erosion Methods= 0
Subcell Deposition Methods= 0
Advection Scheme= 1
Matrix Solver= 0
Implicit Weighting Factor= 1
Maximum Outer Loop Convergence Iterations= 5
Convergence Maximum Absolute= 0.001
Convergence RMSE= 0.0001
Grain Fractions Max Abs Error= 0.001
Max Subgrid Regions= 1
Max Subgrid Length Scale= 3.402823E+38
Initial Layer Thickness= 3.402823E+38
Min Layer Thickness= 3.402823E+38
Max Layer Thickness= 3.402823E+38
Number of Layers= 5

--- BETSYRN.f01 (steady flow) ---

Flow Title=Flow
Program Version=6.31
Number of Profiles= 1
Profile Names=F01pct
River Rch & RM=BETSYRN,Main,4791
     649
River Rch & RM=BETSYRN,Main,2001
     728
Boundary for River Rch & Prof#=BETSYRN,Main            , 1
Up Type= 0
Dn Type= 3
Dn Slope=0.01278
DSS Import GetInterval= 0
DSS Import GetPeak= 0
DSS Import FillOption= 0

--- BETSYRN.g01 (geometry) ---

Geom Title=Geometry
Program Version=6.30

River Reach=BETSYRN         ,Main
Reach XY= 30
     1645536.655      399487.794     1645466.661      399368.849
     1645382.934      399087.324     1645405.971      398985.434
     1645332.654       398766.15     1645339.078      398732.039
     1645423.247      398636.573     1645349.045      398424.377
     1645409.293      398344.637     1645399.104      398302.995
     1645427.234      398197.5621645519.04727034398108.008550427
     1645481.059      397944.167     1645560.134      397881.926
     1645686.388      397503.384     1645791.822      397327.957
     1645870.897      397146.106     1646054.077      396932.802
     1645991.171      396785.062      1646001.36      396748.958
     1645944.435      396685.609     1645961.269      396420.918
     1645918.962      396114.806     1645821.724      396017.125
     1645703.001      395663.612      1645759.04      395548.211
1645720.91652888395361.654734155     1645751.836      395197.361
1645731.32329735395160.0067348091645595.37682349395108.191811751

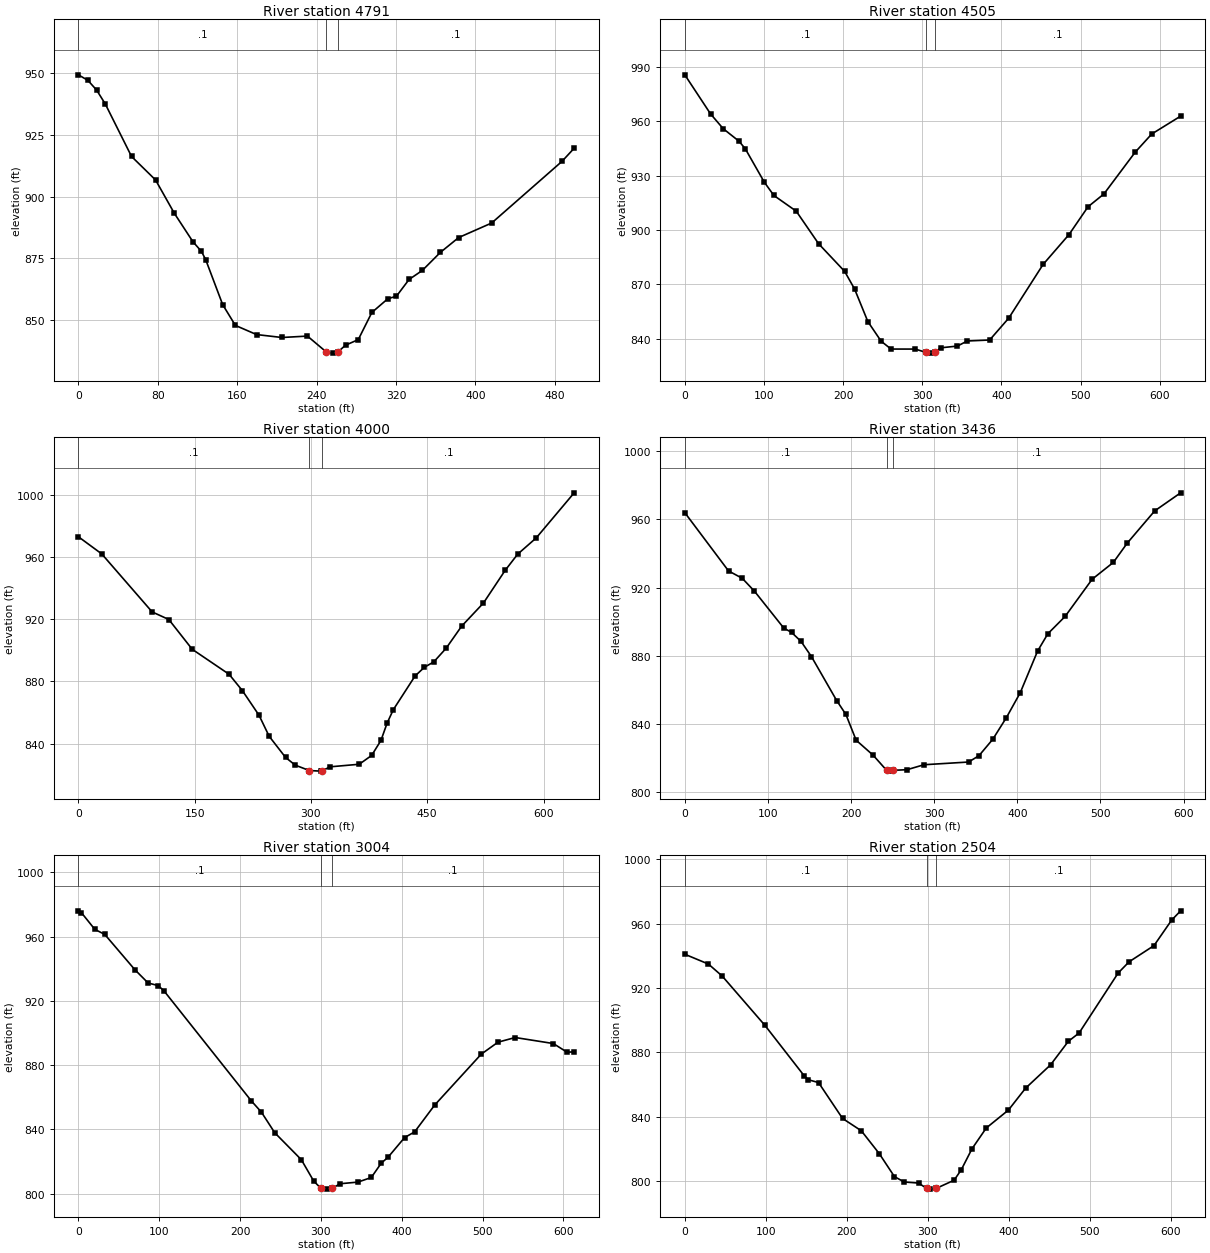
Type RM Length L Ch R = 1 ,4791    ,282.7,285.9,289.7
XS GIS Cut Line= 4
1645680.75773143399203.7604780241645574.09591457399253.339913668
1645359.69360217399333.4178857691645317.15353942399480.369839456
#Sta/Elev= 30
       0  949.23     9.5  947.04    18.4  943.08    27.2  937.41    53.6  916.22
    77.8  906.72    96.7  893.25   115.4  881.77     124  877.84   128.3   874.5
   145.4  856.32   158.2  847.91   179.5  844.21   205.1  843.02   230.8  843.59
   249.7837.2036   256.4   836.7   261.5  837.19   269.2  839.91     282  842.16
   295.7  853.14   311.9  858.73   320.4  859.68   333.2  866.49   346.5  870.12
   364.8  877.46   383.1  883.42   416.4  889.31   487.2  914.22   499.5  919.55
#Mann= 3 ,-1,0
       0      .1       0   249.7    .045       0   261.5      .1       0
Bank Sta=249.7,261.5
XS Rating Curve= 0 ,0
Exp/Cntr(USF)=0,0
Exp/Cntr=0.3,0.1

Type RM Length L Ch R = 1 ,4505    ,508,505.3,501.1
XS GIS Cut Line= 6
1645704.53949559399080.2910482591645608.96422742399076.433444425
1645520.93815675399065.463650092  1645353.002469 399013.26854451
1645183.97262333399001.4342505931645087.22150451399000.636023834
#Sta/Elev= 30
       0  985.72    32.5  964.18    48.5     956    68.5  949.08    76.5  944.86
   100.5  926.44   112.6  919.12   140.8  910.47   169.1  892.48     202  877.23
   214.6  867.44   231.3  849.53   248.1  838.69   260.6  834.37   291.2  834.36
     305832.4871   310.9  832.12   315.6832.4847   323.5  835.06   344.4  836.01
     357  838.82   385.2  839.36   409.3  851.43   452.7  881.05   485.5  897.58
   509.5   912.9   529.6  919.98     569  942.98     590  953.06   626.5  962.92
#Mann= 3 ,-1,0
       0      .1       0     305    .045       0   315.6      .1       0
Bank Sta=305,315.6
XS Rating Curve= 0 ,0
Exp/Cntr(USF)=0,0
Exp/Cntr=0.3,0.1

Type RM Length L Ch R = 1 ,4000    ,554.5,563.6,563.9
XS GIS Cut Line= 6
1645693.78984517398488.4224813431645598.83891959398505.859782428
1645447.29394709398566.7507367581645350.25936426398591.920962006
1645269.47245234398596.0430010111645071.33603759398583.652933925
#Sta/Elev= 30
       0  972.91    30.2  961.85    95.2  924.58   116.7  919.71   146.9  900.57
   194.4  884.53   211.6     874   233.1  858.15   246.1   844.7   267.2  831.14
   279.7  826.14     298822.6637   312.7  822.29   314.8  822.68   325.1  825.07
   362.3  826.71   378.3  832.37   390.3     842   398.3  853.21   406.3  861.81
   434.3  883.41   446.4  889.05   458.4  892.45   474.4  901.25   494.4  915.44
   522.5  930.29   550.5  951.28   566.7  961.71   590.6  972.14   639.5  1001.1
#Mann= 3 ,-1,0
       0      .1       0     298    .045       0   314.8      .1       0
Bank Sta=298,314.8
XS Rating Curve= 0 ,0
Exp/Cntr(USF)=0,0
Exp/Cntr=0.3,0.1

Type RM Length L Ch R = 1 ,3436    ,431.7,432.4,431
XS GIS Cut Line= 4
1645758.74683859398159.0995706191645566.03827123398105.220914495
1645461.86813604398084.3918039141645182.10997405398007.920522157
#Sta/Elev= 30
       0     964    52.6   929.8    69.1  925.48    83.8   917.9     119   896.3
   128.4  893.74   139.8  888.45   152.3  879.56   182.7  853.73   193.8  845.55
   206.1  830.46   226.5  821.68   242.7812.8156   246.9  812.32     251   812.8
   267.3  813.16   287.7  816.07   341.3  817.66   353.8  821.36   370.4  830.97
   386.9  843.78   403.5  858.34   424.3  882.73   436.7  892.94   457.5  903.12
     490  924.93   515.5  934.81   532.3  946.19   565.2  965.02   596.4  975.63
#Mann= 3 ,-1,0
       0      .1       0   242.7    .045       0     251      .1       0
Bank Sta=242.7,251
XS Rating Curve= 0 ,0
Exp/Cntr(USF)=0,0
Exp/Cntr=0.3,0.1

Type RM Length L Ch R = 1 ,3004    ,498.7,500,501.4
XS GIS Cut Line= 6
  1645915.898981397805.0331000831645824.87685335397782.581701428
1645570.01581451397719.7169977581645497.19804676397701.755419508
1645412.28253417397680.6462097621645323.98251392397647.159400091
#Sta/Elev= 30
       0  976.13     3.9  974.92    20.4  964.59    32.7  961.44    69.8  939.53
    86.3  931.19    98.7  929.59     106  926.25     214  857.75   226.4   850.8
   242.9  837.96   275.8  821.17     291  807.96   299.8803.4375   307.6  802.85
   313.8803.4153   324.1  806.22   345.8  807.23   362.3  810.09   374.7  819.07
   382.9  822.63   403.5  834.96   415.9  838.49   440.6  855.13   498.3  886.89
     519  894.34   540.3  897.25   587.4   893.5   604.5  888.08   613.2  888.35
#Mann= 3 ,-1,0
       0      .1       0   299.8    .045       0   313.8      .1       0
Bank Sta=299.8,313.8
XS Rating Curve= 0 ,0
Exp/Cntr(USF)=0,0
Exp/Cntr=0.3,0.1

Type RM Length L Ch R = 1 ,2504    ,507.9,502.6,496.5
XS GIS Cut Line= 6
1646093.99803425397405.4764845071646008.94341435397366.046445251
1645861.51490343397297.701109499  1645702.745864397224.097910255
1645623.36085217397187.2971308381645538.30623226397147.867091596
#Sta/Elev= 30
       0  940.96    29.2  934.85    46.2  927.39    99.1  896.67   147.6   865.3
   152.7   862.9   165.2  861.18   194.9  838.85   218.1  831.18   240.2     817
     259  802.69     271  799.37   288.7  798.69   298.7795.4314   303.4  794.92
   310.7  795.41   332.7  800.46   341.6  807.02   354.8  820.02   372.4  832.92
   399.8  844.08   420.9  857.64   451.8  872.17   473.8  886.82   487.1     892
   535.3  929.26   548.8  936.24   579.6  946.33   601.4  962.16   612.5  967.95
#Mann= 3 ,-1,0
       0      .1       0   298.7    .045       0   310.7      .1       0
Bank Sta=298.7,310.7
XS Rating Curve= 0 ,0
Exp/Cntr(USF)=0,0
Exp/Cntr=0.3,0.1

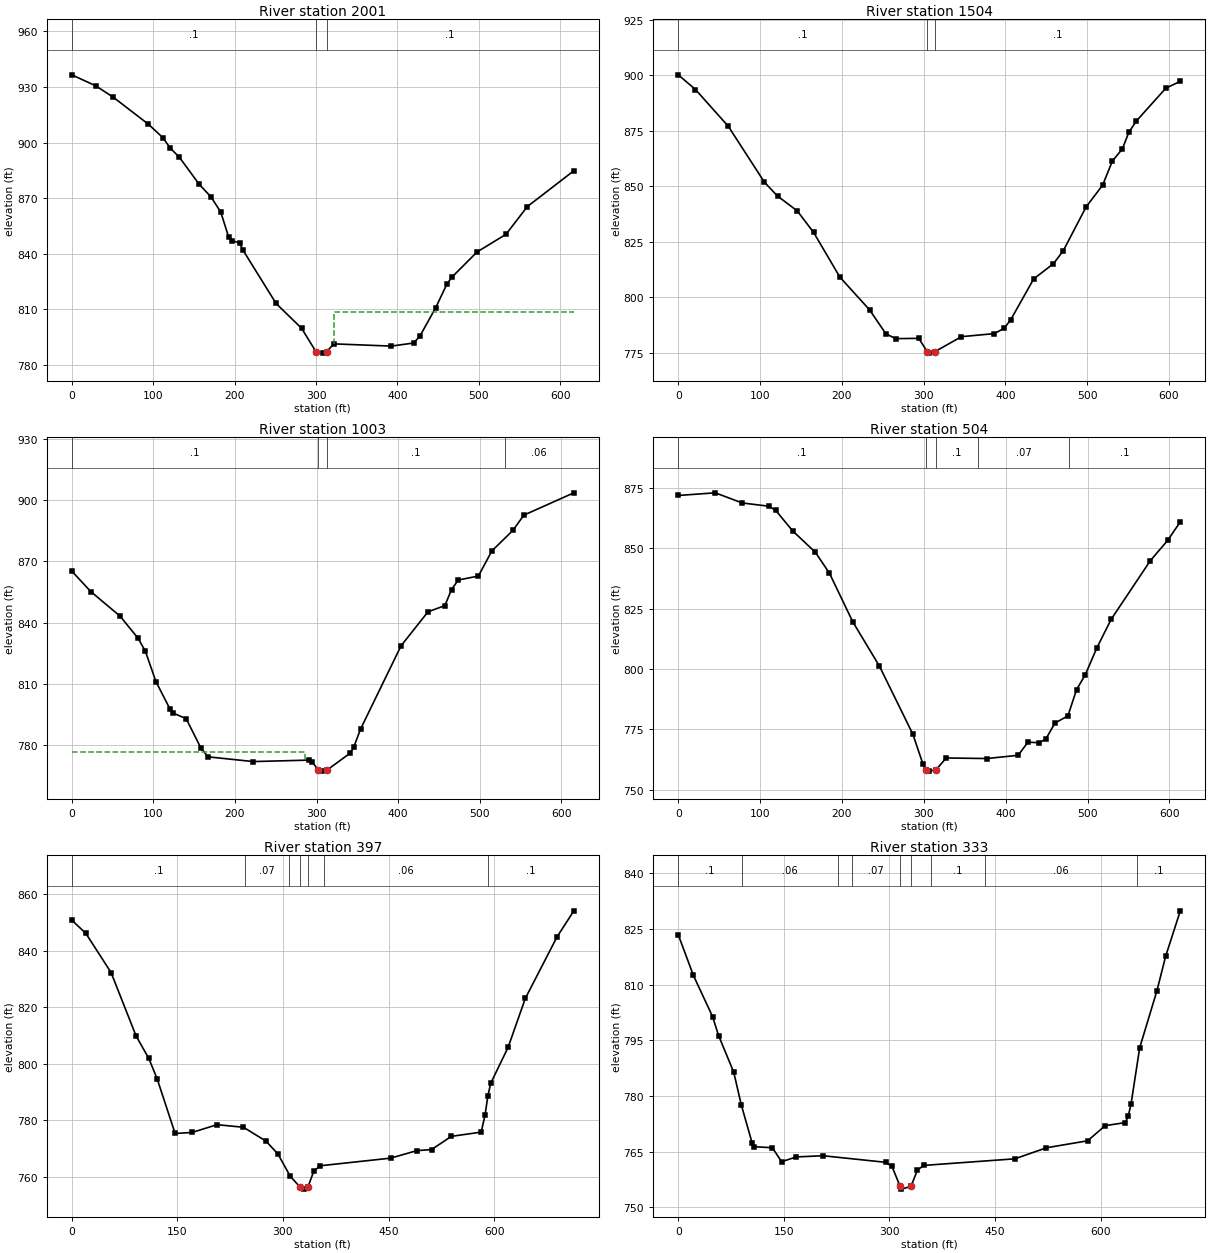
Type RM Length L Ch R = 1 ,2001    ,493.6,497.4,496.7
XS GIS Cut Line= 6
1646311.60258593396734.8108310851646223.83668534396769.237599507
1646145.56617258396808.391720667 1646079.1762135396843.282398924
1645892.83449573396929.0229885581645743.95046179396970.914568449
#Sta/Elev= 30
       0  936.58    29.5  930.63      51  924.49      94  909.95   111.9  902.67
   120.8  897.11   132.3  891.99   156.6  877.43   171.1  870.65     183  862.48
   192.5  849.25     197  847.03     206  845.85   210.5  841.79   250.9   813.2
   282.2  799.79   299.8  787.22   308.6  786.38     313  787.16   321.8  791.38
   392.3  790.17   419.9  791.84   427.5  795.54     447  810.96   460.8  823.74
   466.8  827.35   497.8     841   533.3  850.51   559.4  865.44   616.6  884.79
#Mann= 3 ,-1,0
       0      .1       0   299.8    .045       0     313      .1       0
#XS Ineff= 2 , 0
                             322          808.57
Permanent Ineff=
       F       F
Bank Sta=299.8,313
XS Rating Curve= 0 ,0
Exp/Cntr(USF)=0,0
Exp/Cntr=0.3,0.1

Type RM Length L Ch R = 1 ,1504    ,500.3,500.4,497.3
XS GIS Cut Line= 6
1646265.14401743396381.3915904161646171.65732776396388.568741426
1646084.46458876396395.8699079161645835.65767168396420.265856504
1645748.00463176396425.4049538371645653.16820726396430.739916921
#Sta/Elev= 30
       0  900.21    21.1  893.59    61.2  877.04   105.3  851.91   121.4  845.61
   145.5  838.96   165.6  829.21   197.7   809.1   233.9   794.4     254  783.56
     266   781.4   294.1  781.54   304.4775.6104   306.2  774.88     314  775.58
   346.4  782.29   386.6  783.67   398.6  786.09   406.7  789.96   434.7  808.32
   458.9  815.16   470.9  821.02   498.9  840.78     519  850.54     531  861.45
     543  866.75     551  874.27   559.9  879.26   596.3   894.2     614  897.28
#Mann= 3 ,-1,0
       0      .1       0   304.4    .045       0     314      .1       0
Bank Sta=304.4,314
XS Rating Curve= 0 ,0
Exp/Cntr(USF)=0,0
Exp/Cntr=0.3,0.1

Type RM Length L Ch R = 1 ,1003    ,498.4,499.6,499.4
XS GIS Cut Line= 6
1646097.26935318395844.8293433341646012.52083501395885.863382012
1645859.82166535395941.4472603351645765.49573851395974.659464255
1645692.45881109395993.7375100851645514.53495434396037.025809333
#Sta/Elev= 30
       0  865.21    23.5  855.13    59.1  843.18    81.3  832.32    90.2  825.97
   103.1  811.14   120.2  797.78   124.6  795.61   140.2  792.94   158.5  778.34
     167  774.24   222.3  771.92   290.3  772.63   294.5   771.9   302.1  767.73
   307.2  767.24   312.7767.7319   341.2  776.05   345.4  778.83   353.9  787.83
   403.6  828.67   436.6   845.3   457.2   848.3   465.4  856.19   473.7  860.86
   498.3  862.79   514.8  875.08   540.8  885.25     554  892.62   615.3  903.56
#Mann= 4 ,-1,0
       0      .1       0   302.1    .045       0   312.7      .1       0
  530.54     .06       0
#XS Ineff= 2 , 0
          286.34   776.8
Permanent Ineff=
       F       F
Bank Sta=302.1,312.7
XS Rating Curve= 0 ,0
Exp/Cntr(USF)=0,0
Exp/Cntr=0.3,0.1

Type RM Length L Ch R = 1 ,504     ,108,106.5,104.7
XS GIS Cut Line= 6
1646052.25927259395436.2100818461645960.82966542395457.208399415
1645875.37675235395476.1899887621645703.57788333395509.510460168
1645617.50144503 395540.053133051645492.37545948 395648.56422393
#Sta/Elev= 30
       0   871.8    45.3  872.89    78.1   868.7   110.6  867.35   119.1  865.62
   139.6  857.21   167.6  848.26   184.7  839.63   213.2  819.53   245.8  801.18
   286.6  773.03   298.8   760.8   302.5758.3393   306.9  757.76   315.1  758.38
   327.3   763.2     377  762.97   415.2  764.31   427.2  769.75   440.7  769.51
     449  771.01   460.1  777.63     476  780.62   486.6  791.52   497.2  797.61
   511.4  808.79   528.9   820.6   576.6  844.79   597.8  853.18   613.3  860.91
#Mann= 5 ,-1,0
       0      .1       0   302.5    .045       0   315.1      .1       0
  366.35     .07       0  477.68      .1       0
Bank Sta=302.5,315.1
XS Rating Curve= 0 ,0
Exp/Cntr(USF)=0,0
Exp/Cntr=0.3,0.1

Type RM Length L Ch R = 1 ,397     ,62.5,63.9,59.9
XS GIS Cut Line= 6
1645990.26737429395401.921802088 1645881.3866054395303.510337898
1645675.14130279 395422.860411491645623.84170976395444.845951363
1645486.69381817395475.2069349961645459.47362595395603.979382819
#Sta/Elev= 30
       0  850.79      20  846.11    55.8  832.27    91.5  809.77   109.4  801.93
   121.5  794.54   146.8  775.37   170.9  775.73   206.3  778.48   243.9  777.57
     276  772.65   292.9   768.1   310.4  760.23   324.1756.4891   330.2   755.7
   335.5756.4789   343.7  761.98   352.7  763.95   453.1  766.66     490   769.3
   511.1  769.68   539.2  774.36   581.6  775.85   587.1  781.96   591.1  788.73
   595.2  793.16   619.8  805.82   644.3  823.14   689.3  844.86   713.2  854.08
#Mann= 7 ,-1,0
       0      .1       0  246.76     .07       0  308.74      .1       0
   324.1    .045       0   335.5      .1       0  358.74     .06       0
  591.61      .1       0
Bank Sta=324.1,335.5
XS Rating Curve= 0 ,0
Exp/Cntr(USF)=0,0
Exp/Cntr=0.3,0.1

Type RM Length L Ch R = 1 ,333     ,213.2,215.8,218.4
XS GIS Cut Line= 6
1645986.60311765395346.9579524081645877.72234876395248.546488217
1645671.47704615 395367.896561811645620.17745311395389.882101682
1645483.02956153395420.243085315 1645455.8093693395549.015533139
#Sta/Elev= 30
       0  823.48    21.5   812.5    48.8  801.38    57.3  796.28    78.8  786.42
    89.6  777.57     105  767.29   108.3  766.32   133.7  766.03   146.8  762.27
   167.7  763.56   205.7  763.88   294.6  762.11   303.6  761.01   315.2755.6241
   317.1  754.88   330.7755.6238   339.6  759.97   348.6  761.27   478.1  763.05
   523.1  766.03   581.6  767.91   606.4  771.99   635.1  772.81   639.1   774.5
   643.2   777.8   655.5  792.99     680  808.36   692.3  817.61   713.2   829.9
#Mann= 9 ,-1,0
       0      .1       0      90     .06       0  226.76      .1       0
  246.76     .07       0   315.2    .045       0   330.7     .07       0
  358.74      .1       0  435.33     .06       0  651.61      .1       0
Bank Sta=315.2,330.7
XS Rating Curve= 0 ,0
Exp/Cntr(USF)=0,0
Exp/Cntr=0.3,0.1

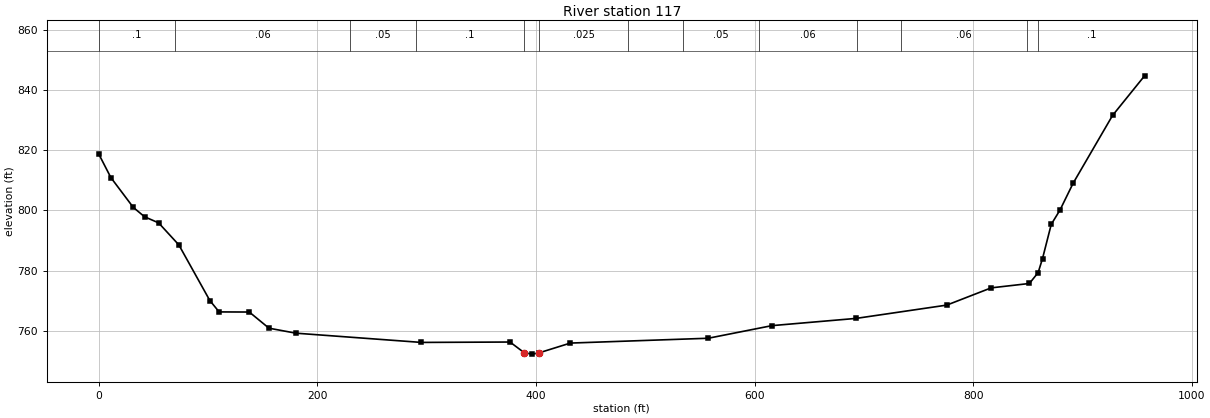
Type RM Length L Ch R = 1 ,117     ,,,
XS GIS Cut Line= 5
1646020.62835793395330.7305301211645765.17732322 395125.53215798
1645639.54566681395178.9256119551645402.35775252395482.509598152
 1645399.4625374395589.994459749
#Sta/Elev= 30
       0  818.68    10.9  810.96    31.4  801.04    41.7  797.91    54.6  795.87
    73.1  788.54   101.5  769.99     110  766.21   137.6  766.17   155.6  760.79
   180.2  759.13     295  756.05   376.2  756.18   389.3752.5909   396.7  752.15
   402.7  752.57   431.4  755.83   557.6  757.44   615.9  761.64   692.9  764.05
   775.9  768.48   816.5  774.22   851.5  775.68   859.5  779.31   863.5  783.97
   871.5  795.38   879.5  800.14   891.5  809.06   927.6  831.65   956.9  844.85
#Mann= 13 ,-1,0
       0      .1       0      70     .06       0     230     .05       0
     290      .1       0   389.3    .045       0   402.7    .025       0
  484.17      .1       0  534.17     .05       0  604.17     .06       0
  694.17     .05       0  734.17     .06       0  849.42     .07       0
  859.42      .1       0
Bank Sta=389.3,402.7
XS Rating Curve= 0 ,0
Exp/Cntr(USF)=0,0
Exp/Cntr=0.3,0.1
LCMann Table=0

Chan Stop Cuts=-1
Use User Specified Reach Order=0
Composite Channel Slope=5